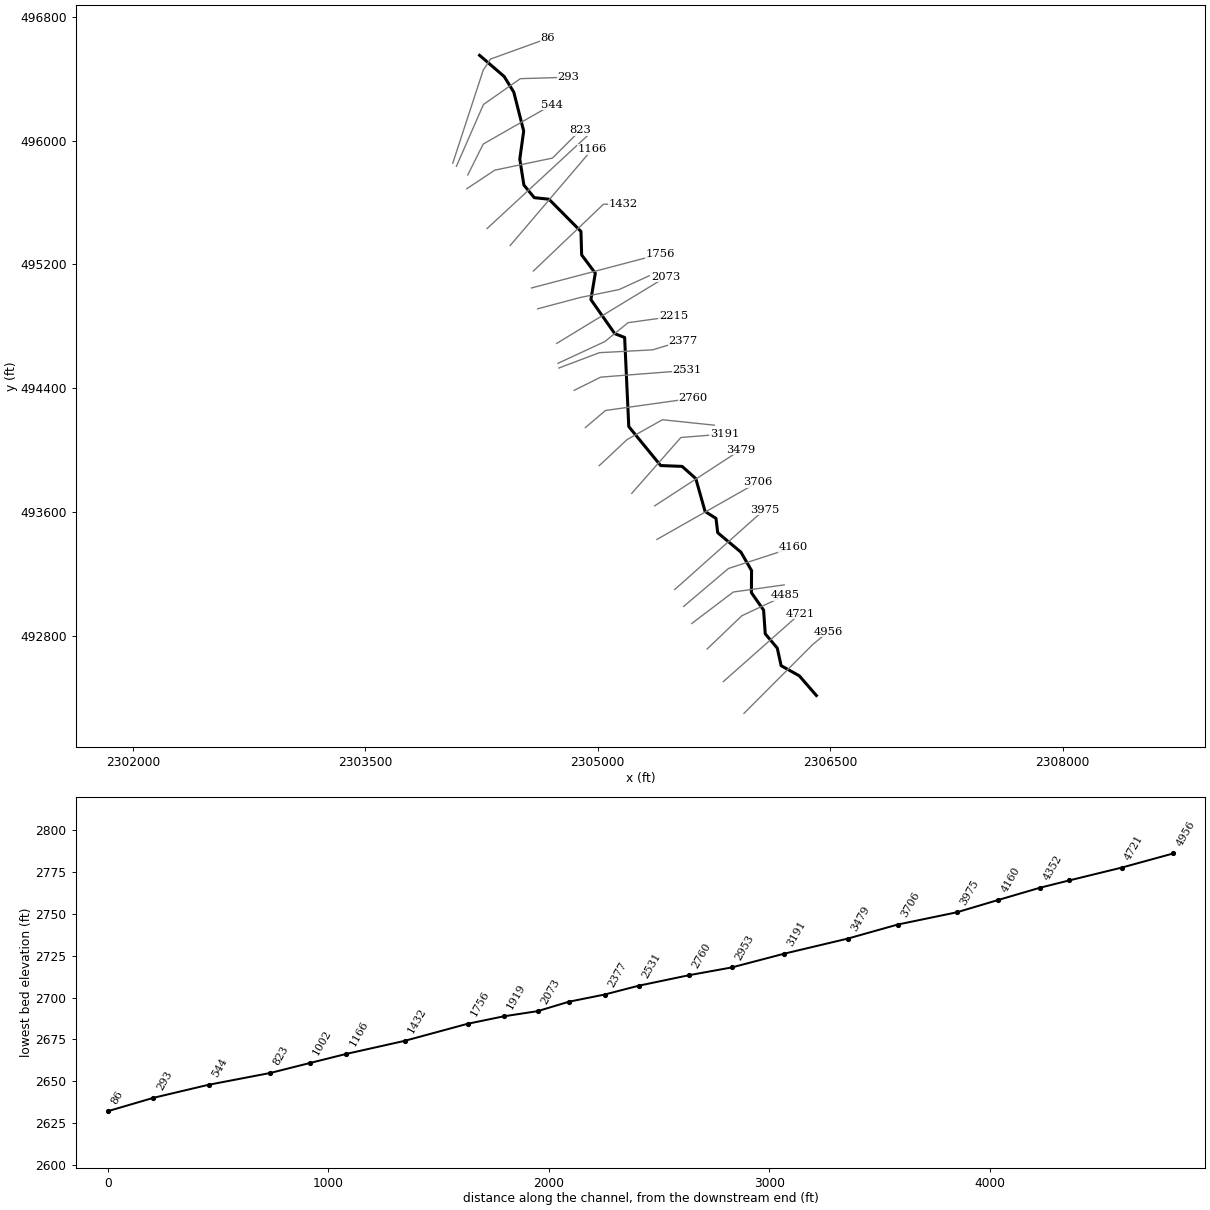
--- JAKESRN.prj (project) ---

Proj Title=JAKESRN
Current Plan=p01
Default Exp/Contr=0,0
English Units
Geom File=g01
Flow File=f01
Plan File=p01
Background Map Layer=Inundation Boundary (01pct Value_0)
BEGIN DESCRIPTION:
----------MODEL BY WOOD PLC 2021----------
Stream Name: Jakes Run
Flood Zone: Approximate
Pocahontas County, WV
HEC-RAS Version: RAS 6.1
Vertical Datum: NAVD88
Projection: NAD 1983 StatePlane West Virginia S FIPS 4702 (US Feet)
Terrain: 1-meter LIDAR (FEMA Region III 3DEP collected 2016-2018)
Land Use: 2019 NLCD
Hydrologic Method:
WV SIR2010-5033 regression equations
Model Notes:
END DESCRIPTION:
DSS Export Rating Curves= 0
DSS Export Rating Curve Sorted= 0
DSS Export Volume Flow Curves= 0
DXF OffsetX= 0
DXF OffsetY= 0
DXF ScaleX= 0
DXF ScaleY= 0

--- JAKESRN.p01 (plan) ---

Plan Title=Floodplain
Program Version=6.00
Short Identifier=Floodplain
Geom File=g01
Flow File=f01
Subcritical Flow
K Sum by GR= 0
Std Step Tol= 0.01
Critical Tol= 0.01
Num of Std Step Trials= 20
Max Error Tol= 0.3
Flow Tol Ratio= 0.001
Split Flow NTrial= 30
Split Flow Tol= 0.02
Split Flow Ratio= 0.02
Log Output Level= 0
Friction Slope Method= 1
Unsteady Friction Slope Method= 2
Unsteady Bridges Friction Slope Method= 1
Parabolic Critical Depth
Global Vel Dist= 0 , 0 , 0
Global Log Level= 0
CheckData=True
Encroach Param=-1 ,0,0, 0
Mapping Interval=1HOUR
Computation Time Step Use Courant=        0
Computation Time Step Use Time Series=    0
Computation Time Step Count To Double=0
Computation Time Step Max Doubling=0
Computation Time Step Max Halving=0
Computation Time Step Residence Courant=0
Run HTab= 0
Run UNet= 0
Run Sediment= 0
Run PostProcess= 0
Run WQNet= 0
Run RASMapper=-1
UNET Theta= 0
UNET Theta Warmup= 0
UNET ZTol= 0
UNET ZSATol= 0
UNET MxIter= 0
UNET Max Iter WO Improvement= 0
UNET MaxInSteps= 0
UNET DtIC= 0
UNET DtMin= 0
UNET MaxCRTS= 0
UNET WFStab= 0
UNET SFStab= 0
UNET WFX= 1
UNET SFX= 1
UNET Gravity=32.174
UNET 1D Methodology=Finite Difference
UNET DSS MLevel= 1
UNET Pardiso=0
UNET DZMax Abort= 0
UNET Use Existing IB Tables= 0
UNET Froude Reduction=False
UNET Froude Limit= 0
UNET Froude Power= 0
UNET D1 Cores= 0
UNET WindReference=Eulerian
UNET WindDragFormulation=Hsu (1988)
UNET D2 Coriolis=0
UNET D2 Cores= 0
UNET D2 Theta= 1
UNET D2 Theta Warmup= 1
UNET D2 Z Tol= 0.01
UNET D2 Volume Tol= 0.01
UNET D2 Max Iterations= 20
UNET D2 Equation= 0
UNET D2 RampUpFraction=0.1
UNET D2 TimeSlices= 1
UNET D2 Turbulence Formulation=Non-Conservative (original)
UNET D2 Eddy Viscosity=0.3
UNET D2 Transverse Eddy Viscosity=0.1
UNET D2 Smagorinsky Mixing=0
UNET D2 BCVolumeCheck=0
UNET D2 Cores=0
UNET D2 SolverType=PARDISO (Direct)
UNET D2 Minimum Iterations= 2147483647
UNET D2 Maximum Iterations= 2147483647
UNET D2 Restart Number= 10
UNET D2 Relaxation Coeff=1.3
UNET D2 SOR Precondition Iterations= 10
UNET D2 ILUT Maximum Fill= 8
UNET D2 ILUT Tolerance=1E-08
UNET D1D2 MaxIter= 0
UNET D1D2 ZTol=0.01
UNET D1D2 QTol=0.1
UNET D1D2 MinQTol=1
Write IC File= 0
Write IC File at Fixed DateTime=0
Write IC File at Sim End=0
Echo Input=False
Echo Parameters=False
Echo Output=False
Write Detailed= 0
HDF Write Warmup=0
HDF Write Time Slices=0
HDF Flush=0
HDF Compression= 1
HDF Chunk Size= 1
HDF Spatial Parts= 1
HDF Use Max Rows=0
HDF Fixed Rows= 1
Calibration Method= 0
Calibration Iterations= 20
Calibration Max Change=0.05
Calibration Tolerance=0.2
Calibration Maximum=1.5
Calibration Minimum=0.5
Calibration Optimization Method= 1
WQ AD Non Conservative
WQ ULTIMATE=-1
WQ Max Comp Step=1HOUR
WQ Output Interval=15MIN
WQ Output Selected Increments= 0
WQ Output face flow=0
WQ Output face velocity=0
WQ Output face area=0
WQ Output face dispersion=0
WQ Output cell volume=0
WQ Output cell surface area=0
WQ Output cell continuity=0
WQ Output cumulative cell continuity=0
WQ Output face conc=0
WQ Output face dconc_dx=0
WQ Output face courant=0
WQ Output face peclet=0
WQ Output face adv mass=0
WQ Output face disp mass=0
WQ Output cell mass=0
WQ Output cell source sink temp=0
WQ Output nsm pathways=0
WQ Output nsm derived pathways=0
WQ Create Restart=0
WQ Fixed Restart=0
WQ System Summary=0
WQ Write To DSS=0
Sorting and Armoring Iterations= 10
XS Update Threshold= 0.02
Bed Roughness Predictor= 0
Hydraulics Update Threshold= 0.02
Energy Slope Method= 1
Volume Change Method= 1
Sediment Retention Method= 0
Sediment TS Multiplier= 1
Warm Up Method= 0
XS Weighting Method= 0
Number of US Weighted Cross Sections= 1
Number of DS Weighted Cross Sections= 1
Upstream XS Weight=0
Main XS Weight=1
Downstream XS Weight=0
Number of DS XS's Weighted with US Boundary= 1
Upstream Boundary Weight= 1
Weight of XSs Associated with US Boundary= 0
Number of US XS's Weighted with DS Boundary= 1
Downstream Boundary Weight= 0.5
Weight of XSs Associated with DS Boundary= 0.5
Percentile Method= 0
Sediment Output Level= 3
Mass or Volume Output= 0
Output Increment Type= 1
Profile and TS Output Increment= 1
Transport Output Increment 1
XS Output Flag= 0
XS Output Increment= 10
Read HDF5 Sediment Hotstart= 0
Sediment Hotstart Type= 0
Write Gradation File= 0
Read Gradation Hotstart= 0
Write HDF5 File= 1
Write Binary Output= 1
Write DSS Sediment File= 0
DSS Sediment Output Type= 1
SV Curve= 0
Specific Gage Flag= 0
Subcell Erosion Methods= 0
Subcell Deposition Methods= 0
Advection Scheme= 1
Matrix Solver= 0
Implicit Weighting Factor= 1
Maximum Outer Loop Convergence Iterations= 5
Convergence Maximum Absolute= 0.001
Convergence RMSE= 0.0001
Grain Fractions Max Abs Error= 0.001
Max Subgrid Regions= 1
Max Subgrid Length Scale= 3.402823E+38
Initial Layer Thickness= 3.402823E+38
Min Layer Thickness= 3.402823E+38
Max Layer Thickness= 3.402823E+38
Number of Layers= 5

--- JAKESRN.f01 (steady flow) ---

Flow Title=Flow
Program Version=6.00
Number of Profiles= 6
Profile Names=01pct,10pct,04pct,02pct,0_2pct,01plus
River Rch & RM=JAKESRN,Main            ,4956
     668     355     471     566     930     988
Boundary for River Rch & Prof#=JAKESRN,Main            , 1
Up Type= 0
Dn Type= 3
Dn Slope=0.03861
Boundary for River Rch & Prof#=JAKESRN,Main            , 2
Up Type= 0
Dn Type= 3
Dn Slope=0.03861
Boundary for River Rch & Prof#=JAKESRN,Main            , 3
Up Type= 0
Dn Type= 3
Dn Slope=0.03861
Boundary for River Rch & Prof#=JAKESRN,Main            , 4
Up Type= 0
Dn Type= 3
Dn Slope=0.03861
Boundary for River Rch & Prof#=JAKESRN,Main            , 5
Up Type= 0
Dn Type= 3
Dn Slope=0.03861
Boundary for River Rch & Prof#=JAKESRN,Main            , 6
Up Type= 0
Dn Type= 3
Dn Slope=0.03861
DSS Import GetInterval= 0
DSS Import GetPeak= 0
DSS Import FillOption= 0

--- JAKESRN.g01 (geometry) ---

Geom Title=Geometry
Program Version=6.10

River Reach=JAKESRN         ,Main
Reach XY= 30
2306411.16512577492417.5161224312306300.63716115492544.878176451
2306183.51254047492610.1323921232306158.56103818492723.488181561
2306080.95155774 492816.023278432306070.32406254492968.859533861
2305991.51989125493081.5085131972305992.71094783493223.879408479
2305923.80275936 493343.147871452305774.17374592493468.449216694
 2305763.1230381493560.7755077482305692.61729015493605.649913311
2305632.53899999493818.0500000122305544.34053425493896.551750571
     2305405.913 493901.951000022305200.06100003494153.547000021
2305173.33000003494728.6490000192305109.88500004      494753.125
2304955.54667686494973.348863944     2304984.156495143.623000011
2304895.89500003 495261.554000022304891.34300004495413.024000004
2304684.85200004495621.0910000062304590.00035746495631.077873975
2304522.95713033495712.6043976842304496.66271515  495880.2197299
2304521.77874641496061.3654390422304457.77279143496312.394936517
2304395.79633893 496413.266829642304237.00700004496549.917999998

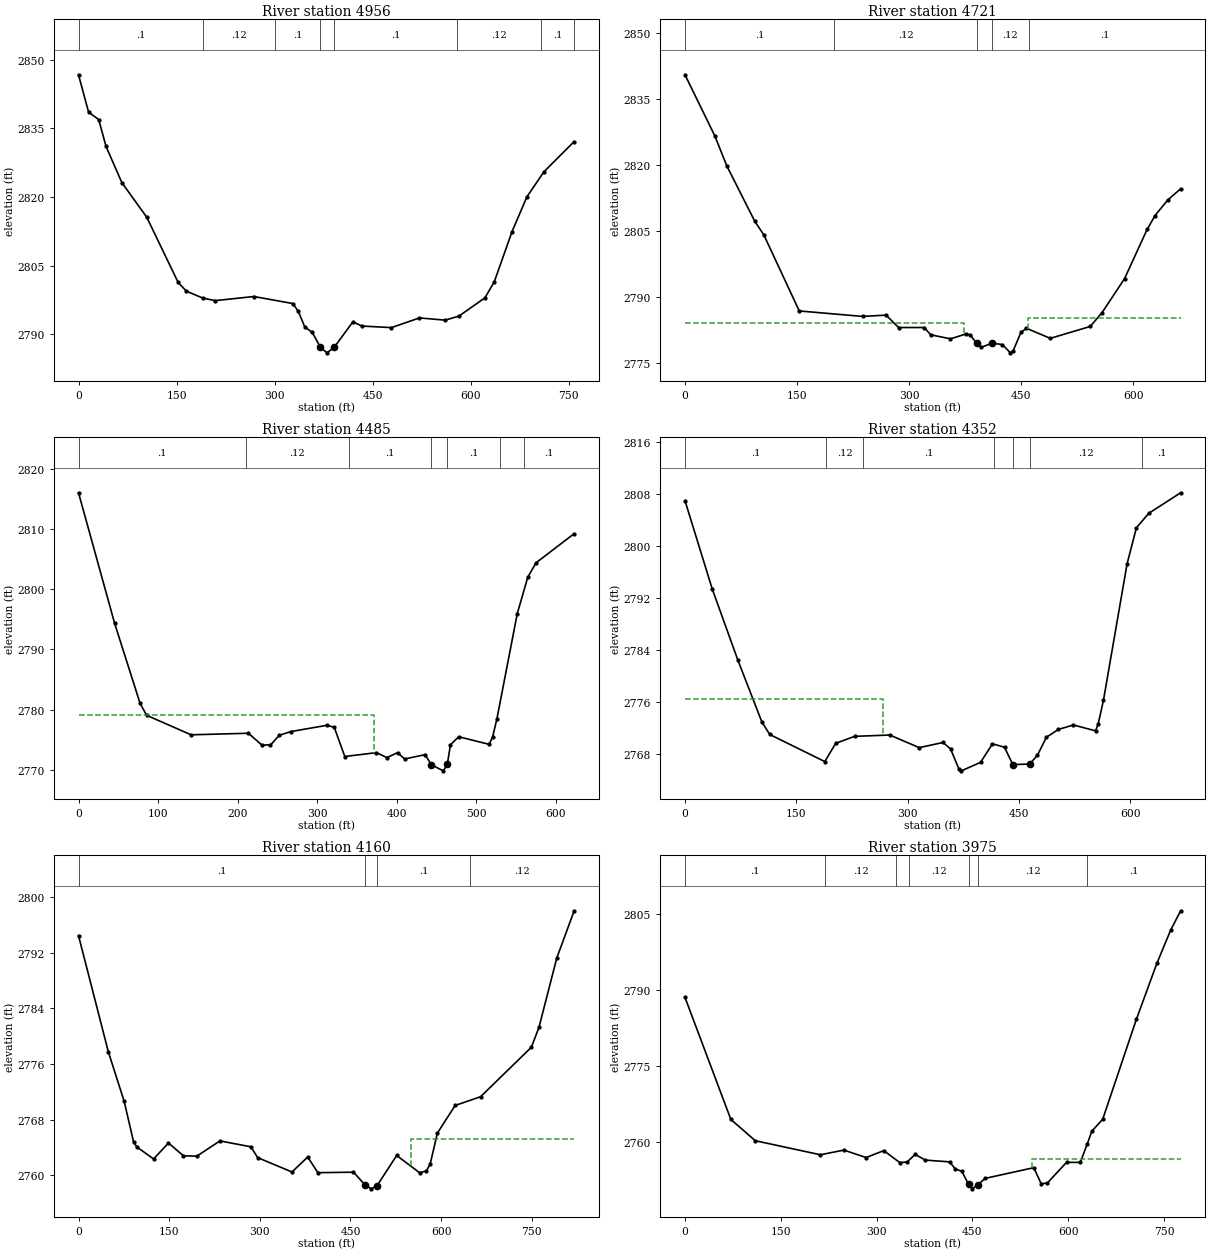
Type RM Length L Ch R = 1 ,4956    ,236.6,235.3,234.3
XS GIS Cut Line= 3
2305943.43566764492302.2885206032306387.23136503492746.568786837
2306487.98074099492829.719149335
#Sta/Elev= 30
       0 2846.73    15.4 2838.56    30.9 2836.93    42.2 2831.04    66.3 2823.14
   104.4 2815.58   152.5  2801.3   165.2 2799.38     1902797.899     209 2797.32
   268.4 2798.22   327.8 2796.69   336.3 2795.02   346.3 2791.56   357.6 2790.39
   370.3 2787.11   380.3  2785.9   391.6 2787.15   419.9 2792.69   433.8 2791.76
     479 2791.42   521.8 2793.54   561.4 2793.05   582.4 2793.95     622 2797.93
   636.2 2801.39   663.5 2812.41   686.2 2820.01   712.2 2825.49   758.6 2832.12
#Mann= 8 ,-1,0
       0      .1       0     190     .12       0     300      .1       0
   370.3    .045       0   391.6      .1       0     580     .12       0
  707.96      .1       0  757.96     .12       0
Bank Sta=370.3,391.6
XS Rating Curve= 0 ,0
Exp/Cntr=0.3,0.1

Type RM Length L Ch R = 1 ,4721    ,239.9,236.2,230.7
XS GIS Cut Line= 2
2305810.26388417492507.2579367462306306.71586842492946.907634463
#Sta/Elev= 30
       0 2840.55      40 2826.65      56 2819.85    93.4 2807.28   105.5  2804.2
   152.9 2786.93   237.6 2785.69   269.1 2785.98   285.7 2783.17   320.1 2783.17
   328.7 2781.52   355.2  2780.6   376.6 2781.74   381.9 2781.43  390.182779.588
   396.6 2778.68   410.8 2779.62   424.7  2779.3   435.3 2777.42   439.1 2777.91
   449.4 2782.05   456.7    2783   488.8 2780.71   542.2 2783.41     558 2786.56
   588.1 2794.28   618.3 2805.45   628.9  2808.6   645.9 2812.13   663.1 2814.66
#Mann= 5 ,-1,0
       0      .1       0     200     .12       0  390.18    .045       0
   410.8     .12       0     460      .1       0
#XS Ineff= 2 , 0
          372.68 2784.17  458.25         2785.28
Permanent Ineff=
       F       F
Bank Sta=390.18,410.8
XS Rating Curve= 0 ,0
Exp/Cntr(USF)=0,0
Exp/Cntr=0.3,0.1

Type RM Length L Ch R = 1 ,4485    ,137.8,133.5,127.9
XS GIS Cut Line= 3
2305706.07561271492717.8608842522305929.54868588492932.139039966
2306212.89872239493065.589103605
#Sta/Elev= 30
       0 2815.99    45.3 2794.35    77.4 2781.01    85.7 2779.04   141.5 2775.81
   213.5 2776.07   230.2 2774.13   241.2 2774.12   252.3 2775.73   266.9 2776.35
   312.5  2777.4   321.4 2777.03   334.6 2772.21   374.4 2772.85   387.5 2772.03
   400.9 2772.85   409.8  2771.8   435.6 2772.52  443.262770.843   458.4 2769.83
   463.4 2770.89   467.3 2774.15   477.7 2775.49   515.9 2774.23   520.3 2775.43
   525.8 2778.51   551.3 2795.93   564.5 2801.97   574.9 2804.37   622.8  2809.2
#Mann= 7 ,-1,0
       0      .1       0     210     .12       0  339.61      .1       0
  443.26    .045       0   463.4      .1       0  529.61     .12       0
  559.61      .1       0
#XS Ineff= 2 , 0
          370.93 2779.02
Permanent Ineff=
       F       F
Bank Sta=443.26,463.4
XS Rating Curve= 0 ,0
Exp/Cntr=0.3,0.1

Type RM Length L Ch R = 1 ,4352    ,187.2,191.3,195
XS GIS Cut Line= 3
2305606.81176937492882.6169889232305874.88246314 493085.65278065
2306203.22940757493131.653077213
#Sta/Elev= 30
       0 2806.92    36.8 2793.34    71.3 2782.43   103.6 2772.95   114.2 2771.03
   188.4 2766.87     203 2769.67   228.4 2770.74   275.9 2770.95   315.6 2769.01
   347.6  2769.8   357.8 2768.82   368.9 2765.78   372.4 2765.45   398.2 2766.75
   414.3  2769.6   430.5 2769.07   441.7 2766.41   464.5 2766.49   474.9 2767.85
     487 2770.61   503.2 2771.81   523.4 2772.49   553.1 2771.59   556.7 2772.64
   563.8 2776.26   595.6  2797.2   608.2 2802.76   624.9 2804.98   667.8 2808.13
#Mann= 7 ,-1,0
       0      .1       0     190     .12       0     240      .1       0
  416.28     .12       0   441.7    .045       0   464.5     .12       0
  616.28      .1       0
#XS Ineff= 2 , 0
          266.28 2776.46
Permanent Ineff=
       F       F
Bank Sta=441.7,464.5
XS Rating Curve= 0 ,0
Exp/Cntr(USF)=0,0
Exp/Cntr=0.3,0.1

Type RM Length L Ch R = 1 ,4160    ,177.4,185.6,193.3
XS GIS Cut Line= 3
2305554.58528341492992.9324568752305843.25579839493237.418028928
2306263.54613066493374.060829145
#Sta/Elev= 30
       0 2794.43    49.3 2777.77    75.5 2770.66    91.2 2764.79    96.4  2764.1
   124.2 2762.37   148.9 2764.66   173.7 2762.81     196 2762.78     234 2764.96
   285.1 2764.12   296.5 2762.56   353.2  2760.5   379.3 2762.65   396.1  2760.4
     455 2760.47   474.1 2758.66   484.4 2758.08     494 2758.53   526.5 2762.87
   564.3  2760.4   575.6 2760.64     582 2761.66   593.8 2766.07   623.2 2770.05
   665.3  2771.3   749.4 2778.41     762 2781.28   791.4 2791.21   820.2    2798
#Mann= 4 ,-1,0
       0      .1       0   474.1    .045       0     494      .1       0
  648.29     .12       0
#XS Ineff= 2 , 0
                          549.83         2765.24
Permanent Ineff=
       F       F
Bank Sta=474.1,494
XS Rating Curve= 0 ,0
Exp/Cntr(USF)=0,0
Exp/Cntr=0.3,0.1

Type RM Length L Ch R = 1 ,3975    ,267.9,268.5,265
XS GIS Cut Line= 2
     2305496.447      493101.4372306075.90701537493617.704433018
#Sta/Elev= 30
       0 2788.57    71.8  2764.5   110.1  2760.3   212.1 2757.53   248.9 2758.45
   283.6 2756.98   311.3 2758.35   336.3 2755.99   347.9 2756.11   360.4  2757.6
   376.4 2756.48   414.5 2756.13   422.9 2754.77   433.6 2754.24   444.12751.698
   449.6 2750.81  459.082751.659   469.9 2752.87   546.1 2754.98   557.8 2751.81
   567.5 2751.97   597.4 2756.03     619 2756.03     6302759.698     637 2762.17
   654.1 2764.54   706.8 2784.24   738.9 2795.29   760.4 2801.81   776.1 2805.65
#Mann= 7 ,-1,0
       0      .1       0     220     .12       0     330      .1       0
     350     .12       0   444.1    .045       0  459.08     .12       0
     630      .1       0
#XS Ineff= 2 , 0
                          543.59         2756.77
Permanent Ineff=
       F       F
Bank Sta=444.1,459.08
XS Rating Curve= 0 ,0
Exp/Cntr=0.3,0.1

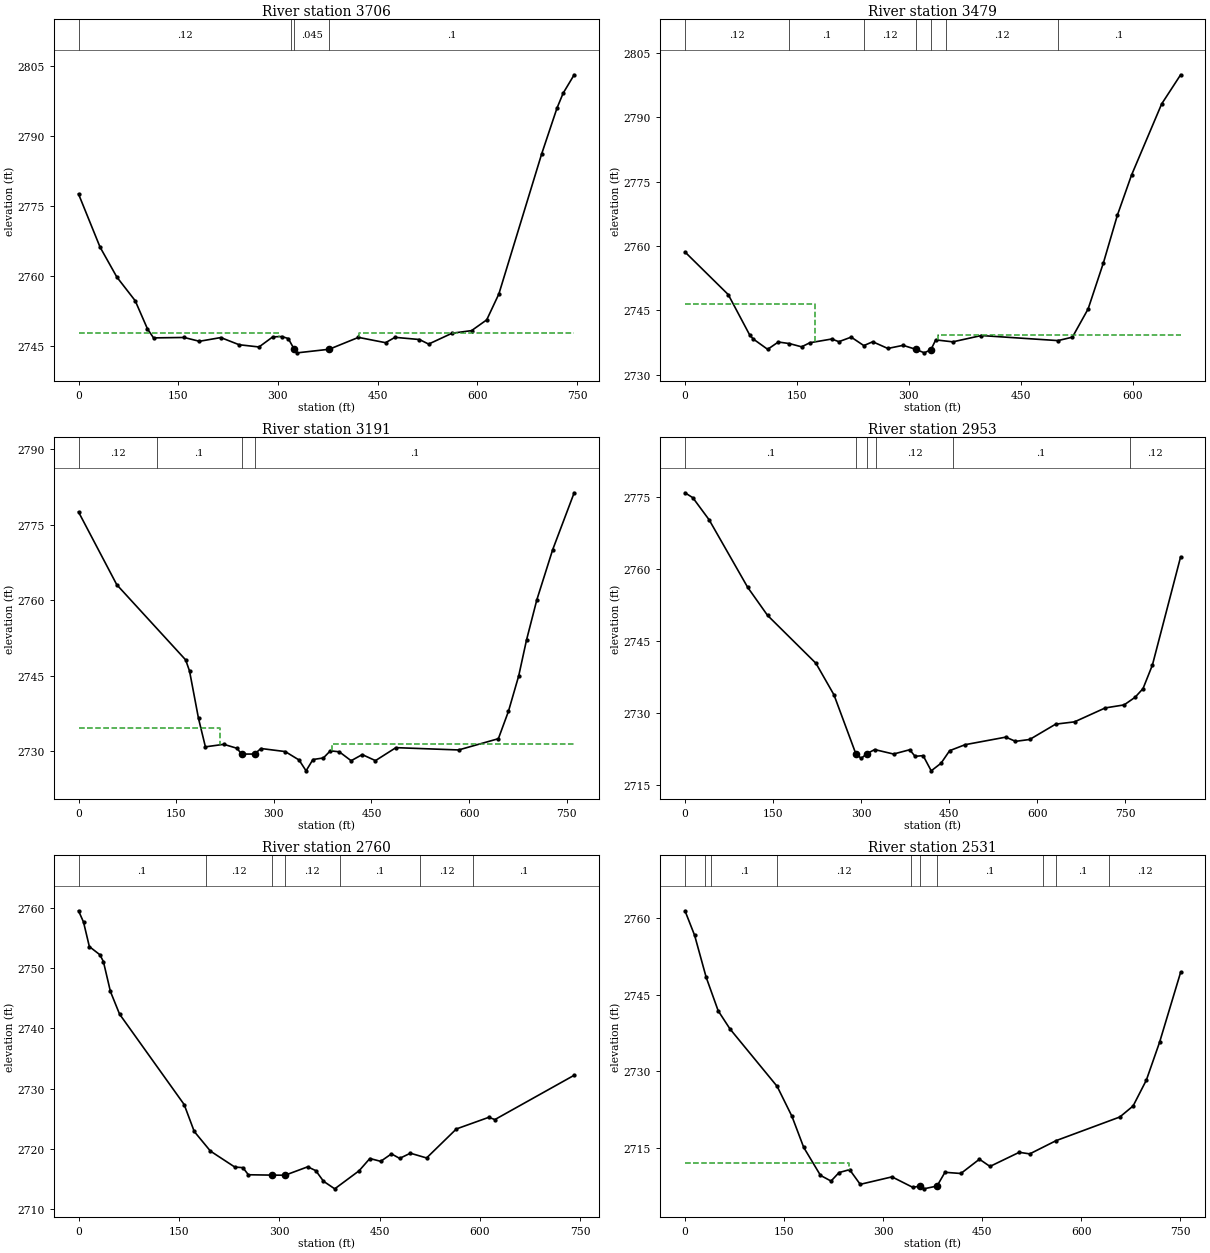
Type RM Length L Ch R = 1 ,3706    ,231.7,226.7,225.9
XS GIS Cut Line= 2
2305381.97464376493425.182887019 2306030.6567559493793.261703713
#Sta/Elev= 30
       0 2777.62    32.4 2766.21    57.7 2759.77    85.3 2754.69   103.7 2748.66
   112.9 2746.71   158.9  2746.8   181.9 2745.98   214.1 2746.78   241.7 2745.24
   271.6 2744.76   292.3 2746.93   306.1    2747   315.6 2746.57   324.2 2744.37
   329.1  2743.5   377.2 2744.27   421.2 2746.82     462 2745.68   476.2 2746.83
     513 2746.36   526.8 2745.38     562 2747.71   591.4 2748.27   614.2 2750.58
   632.5 2756.15     697 2786.27     720 2796.08   729.2 2799.26   745.8 2803.22
#Mann= 4 ,-1,0
       0     .12       0     320      .1       0   324.2    .045       0
   377.2      .1       0
#XS Ineff= 2 , 0
          301.56 2747.67   421.7         2747.82
Permanent Ineff=
       F       F
Bank Sta=324.2,377.2
XS Rating Curve= 0 ,0
Exp/Cntr(USF)=0,0
Exp/Cntr=0.3,0.1

Type RM Length L Ch R = 1 ,3479    ,283.7,288.3,291.3
XS GIS Cut Line= 2
2305367.31257305493641.8279967722305924.13562201494004.344524479
#Sta/Elev= 30
       0 2758.62      58 2748.69    86.9 2739.23    91.7 2738.32   110.8 2735.94
   125.1 2737.64     140 2737.28   156.3 2736.52   167.4 2737.47   196.7 2738.34
   206.3 2737.72   222.8 2738.78   239.7 2736.81   251.7  2737.7   271.9 2736.14
   292.4 2736.87   309.5 2735.93   320.8 2735.12   329.7 2735.86   336.1 2738.14
     359 2737.68   397.2 2739.15     500 2737.97   519.3 2738.77   540.4 2745.35
     561 2756.15   579.6 2767.18   598.6 2776.54     639 2793.12   664.4  2799.9
#Mann= 7 ,-1,0
       0     .12       0     140      .1       0     240     .12       0
   309.5    .045       0   329.7      .1       0     350     .12       0
     500      .1       0
#XS Ineff= 2 , 0
          174.42 2746.56  338.71         2739.22
Permanent Ineff=
       F       F
Bank Sta=309.5,329.7
XS Rating Curve= 0 ,0
Exp/Cntr=0.3,0.1

Type RM Length L Ch R = 1 ,3191    ,242,237.7,231.9
XS GIS Cut Line= 3
2305219.52010429493722.8268684192305536.47686311494082.953364999
2305817.08015856 494105.67427961
#Sta/Elev= 30
       0 2777.58    58.8 2763.11   164.5 2748.18   170.5 2745.98   184.3 2736.54
   194.9 2730.89   223.2 2731.39   243.2 2730.61  250.592729.454  270.422729.457
   280.2 2730.56   317.5 2729.95   338.8 2728.27   349.5 2726.12   360.1 2728.37
   376.1 2728.68   386.8  2730.1   400.6  2729.9   418.7 2728.13   435.8 2729.35
   456.1 2728.15   487.5 2730.73   583.8 2730.27   644.9 2732.51   660.4 2737.97
   676.1 2744.99   688.1 2752.12     704 2760.13   728.3 2770.08   761.3 2781.39
#Mann= 4 ,-1,0
       0     .12       0     120      .1       0  250.59    .045       0
  270.42      .1       0
#XS Ineff= 2 , 0
          216.61 2734.68  388.87         2731.45
Permanent Ineff=
       F       F
Bank Sta=250.59,270.42
XS Rating Curve= 0 ,0
Exp/Cntr(USF)=0,0
Exp/Cntr=0.3,0.1

Type RM Length L Ch R = 1 ,2953    ,198.3,193.1,185.9
XS GIS Cut Line= 4
2305009.34485351493901.1070121442305188.84686957494069.320816233
2305417.19206141494197.6939837832305751.97788102494162.566134348
#Sta/Elev= 30
       0 2775.83    13.4  2774.8    41.1 2770.21   106.8 2756.15   140.7  2750.3
   223.2 2740.32   253.9 2733.75   291.1  2721.5   300.3 2720.53     310  2721.5
   323.2 2722.36   355.4 2721.43   382.9 2722.32   392.1 2720.95   405.8  2721.1
   419.6 2717.93   436.3 2719.51     451 2722.13   477.5 2723.38   546.7 2724.95
   563.2 2724.07   587.4 2724.46   631.6 2727.65   663.8 2728.13   716.1 2731.03
   748.3 2731.66   766.9 2733.24   780.5 2735.05   796.5 2739.96   844.6  2762.5
#Mann= 6 ,-1,0
       0      .1       0   291.1    .045       0     310      .1       0
     326     .12       0     456      .1       0  757.96     .12       0
Bank Sta=291.1,310
XS Rating Curve= 0 ,0
Exp/Cntr=0.3,0.1

Type RM Length L Ch R = 1 ,2760    ,228.9,229.3,225.6
XS GIS Cut Line= 3
2304919.84260104494146.9809023722305049.59038392 494257.40454738
2305614.59136755494336.541492969
#Sta/Elev= 30
       0 2759.53     7.5 2757.65    16.2 2753.58      32 2752.22    37.2 2751.09
    47.7 2746.12    61.4 2742.35   157.9 2727.34     173 2722.86   197.2  2719.6
   233.6 2716.95   245.7 2716.85   253.9 2715.67   289.4 2715.61  308.72 2715.59
   342.6 2716.99   354.7 2716.35   366.2 2714.59     383 2713.33   419.4 2716.33
   435.5 2718.37   451.7  2717.9   467.8 2719.14     480 2718.39   496.1 2719.25
   520.3 2718.46   564.8 2723.28   613.2 2725.21   622.4 2724.84   740.9  2732.2
#Mann= 7 ,-1,0
       0      .1       0  190.38     .12       0   289.4    .045       0
  308.72     .12       0  390.38      .1       0  510.38     .12       0
  590.38      .1       0
Bank Sta=289.4,308.72
XS Rating Curve= 0 ,0
Exp/Cntr(USF)=0,0
Exp/Cntr=0.3,0.1

Type RM Length L Ch R = 1 ,2531    ,154.4,153.9,153.7
XS GIS Cut Line= 3
2304847.14703474494387.1523302652305019.22388154494472.730655146
2305575.94309179494515.979916107
#Sta/Elev= 30
       0 2761.37    14.6 2756.57    32.1 2748.37    50.3 2741.82    68.2 2738.27
   139.6 2727.05     162  2721.2   179.8 2715.13   205.2 2709.66   221.2 2708.55
   233.3 2710.21   249.3 2710.78   265.4 2707.91   313.5 2709.37     345 2707.32
  356.132707.579   361.6 2707.03   381.7 2707.58   393.7 2710.26   417.8 2710.03
   445.9 2712.82   461.9 2711.41   506.2 2714.17   522.1 2713.86  562.182716.459
   658.5 2721.07   678.6 2723.22   698.7 2728.28   718.7 2735.67   750.6 2749.35
#Mann= 10 ,-1,0
       0      .1       0      30     .12       0      40      .1       0
     140     .12       0  342.18      .1       0  356.13    .045       0
   381.7      .1       0  542.18     .12       0  562.18      .1       0
  642.18     .12       0
#XS Ineff= 2 , 0
          249.04 2712.13
Permanent Ineff=
       F       F
Bank Sta=356.13,381.7
XS Rating Curve= 0 ,0
Exp/Cntr(USF)=0,0
Exp/Cntr=0.3,0.1

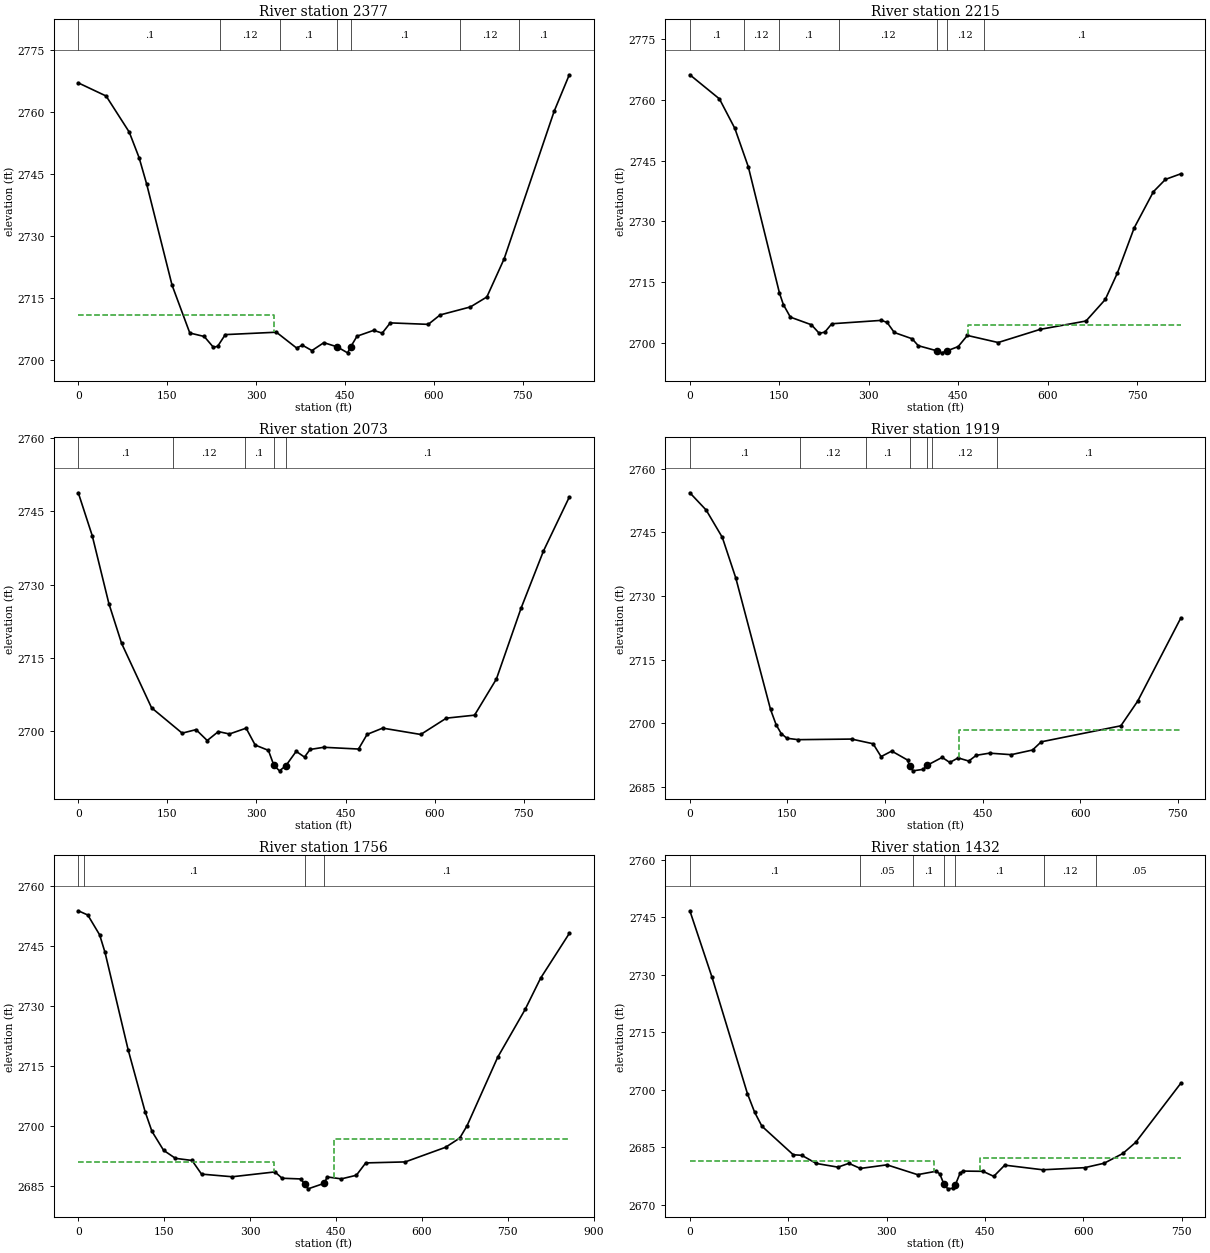
Type RM Length L Ch R = 1 ,2377    ,147.1,162.4,171.9
XS GIS Cut Line= 4
2304748.19168596494531.1546523712305010.48768988494630.527407117
 2305353.5735005494648.7041388062305549.39834156494707.860801706
#Sta/Elev= 30
       0 2767.11      47 2763.93      86  2755.2   102.6 2749.03   115.5 2742.58
   158.2 2718.19   188.2 2706.59   212.5 2705.75     228 2703.14   235.2 2703.37
   248.1  2706.2   334.3 2706.78   368.3 2702.97   378.3 2703.63   394.3 2702.34
   414.4 2704.25  436.882703.243   454.4 2701.79   459.6 2703.21   470.4 2705.82
   498.5 2707.23   512.9 2706.56   526.5 2709.04   590.6 2708.68   610.6 2710.96
   661.8  2712.9   689.5 2715.31   718.7 2724.55     803 2760.22   828.6 2769.07
#Mann= 7 ,-1,0
       0      .1       0     240     .12       0  340.49      .1       0
  436.88    .045       0   459.6      .1       0  644.06     .12       0
  744.06      .1       0
#XS Ineff= 2 , 0
           330.7 2710.99
Permanent Ineff=
       F       F
Bank Sta=436.88,459.6
XS Rating Curve= 0 ,0
Exp/Cntr=0.3,0.1

Type RM Length L Ch R = 1 ,2215    ,143.5,141.6,139.1
XS GIS Cut Line= 4
2304743.22243843494561.9335557532305045.15886777494701.980665531
 2305195.4846645494824.0400731372305489.71207863494865.154820962
#Sta/Elev= 30
       0 2766.24    49.6 2760.28    75.5 2752.97    98.1 2743.46   150.3 2712.28
   156.8 2709.43   168.6 2706.32   203.9 2704.43     217 2702.32   226.4 2702.61
   238.1 2704.68   321.4 2705.52   330.9    2705   342.9 2702.52   372.8 2700.97
   383.1 2699.26   414.1    2698   422.6 2697.49   431.1 2697.96   450.1 2699.04
   465.5 2701.79   517.1 2700.04   587.8  2703.3   664.5 2705.36   696.8 2710.68
     717 2717.18   745.3 2728.38   777.6 2737.34   797.8 2740.38   823.6 2741.76
#Mann= 7 ,-1,0
       0      .1       0      90     .12       0     150      .1       0
     250     .12       0   414.1    .045       0   431.1     .12       0
  492.83      .1       0
#XS Ineff= 2 , 0
                          465.81         2704.34
Permanent Ineff=
       F       F
Bank Sta=414.1,431.1
XS Rating Curve= 0 ,0
Exp/Cntr(USF)=0,0
Exp/Cntr=0.3,0.1

Type RM Length L Ch R = 1 ,2073    ,159.3,154,146.7
XS GIS Cut Line= 2
2304734.73519756494690.393105838     2305441.007      495120.048
#Sta/Elev= 30
       0 2748.77    23.5 2739.99    51.5 2726.11    72.9 2717.97   123.4 2704.78
   174.9 2699.59   198.3 2700.31   217.1 2698.08   235.8 2699.91   254.5 2699.42
   282.6 2700.61   297.8 2697.16   320.1 2696.07   329.4 2692.99   338.8 2691.88
   349.5 2692.93   366.9 2695.87   380.9 2694.69   390.2 2696.25   413.3  2696.7
   471.8 2696.34   486.3 2699.34   512.5 2700.62   576.6 2699.32   619.7 2702.66
   667.2 2703.27     704 2710.67   745.4 2725.12   783.2 2736.85   826.7 2747.89
#Mann= 5 ,-1,0
       0      .1       0     160     .12       0     280      .1       0
   329.4    .045       0   349.5      .1       0
Bank Sta=329.4,349.5
XS Rating Curve= 0 ,0
Exp/Cntr=0.3,0.1

Type RM Length L Ch R = 1 ,1919    ,152.9,163.1,158.8
XS GIS Cut Line= 4
 2304611.9607806494913.634295911  2304885.259302494986.329862208
2305137.39329144495037.8608965462305332.47506428495127.120009594
#Sta/Elev= 30
       0 2754.35    25.1 2750.27    49.9 2743.83    70.6 2734.26     124 2703.27
   132.7 2699.62   140.4 2697.58   149.2 2696.47   166.5 2696.14   248.6 2696.28
   281.7 2695.17   293.9 2692.14   310.3 2693.45   334.8 2691.32  337.73 2689.93
   342.9 2688.79   358.9 2689.15  364.492690.078   387.8 2691.96   399.6 2690.76
   412.3 2691.84   428.7  2691.1   440.2 2692.45   460.6 2692.96     494  2692.6
   526.7  2693.7   540.1 2695.63   662.5 2699.41   688.4 2705.24   754.7 2724.85
#Mann= 7 ,-1,0
       0      .1       0     170     .12       0     270      .1       0
  337.73    .045       0  364.49      .1       0   372.8     .12       0
   472.8      .1       0
#XS Ineff= 2 , 0
                          413.29         2698.34
Permanent Ineff=
       F       F
Bank Sta=337.73,364.49
XS Rating Curve= 0 ,0
Exp/Cntr(USF)=0,0
Exp/Cntr=0.3,0.1

Type RM Length L Ch R = 1 ,1756    ,283.4,286.1,284.7
XS GIS Cut Line= 2
2304572.08140902495048.1986405222305401.12987081495266.369288362
#Sta/Elev= 30
       0 2753.85    16.6 2752.79    37.3 2747.83    46.7 2743.44      87 2719.15
   116.6 2703.68   128.6 2698.73     149 2693.98   169.7 2691.98   198.6 2691.45
   215.2 2688.04   268.9 2687.38   343.4 2688.59   355.8 2687.01   388.9 2686.83
  394.992685.521   401.3 2684.36   429.8 2685.76   434.4 2687.34   459.3 2686.85
   485.5 2687.75   501.9 2690.84   570.9 2691.09   641.2 2694.74     666 2697.04
   678.7  2700.1   732.2 2717.22   780.2 2729.19   807.1 2736.98   857.3 2748.19
#Mann= 4 ,-1,0
       0     .12       0      10      .1       0  394.99    .045       0
   429.8      .1       0
#XS Ineff= 2 , 0
          341.97 2691.06  446.84         2696.78
Permanent Ineff=
       F       F
Bank Sta=394.99,429.8
XS Rating Curve= 0 ,0
Exp/Cntr(USF)=0,0
Exp/Cntr=0.3,0.1

Type RM Length L Ch R = 1 ,1432    ,263.1,266,267.8
XS GIS Cut Line= 3
 2304584.6436212495157.7590511092305036.49871493495588.456948115
2305161.16085977495589.228778772
#Sta/Elev= 30
       0  2746.7    33.9 2729.32    87.8 2699.01    98.8 2694.15   109.9 2690.51
   157.7 2683.06   170.7 2682.92   192.8 2680.79   225.9 2679.83   242.5 2680.82
     260 2679.49   300.6 2680.43   347.3 2677.87     376 2678.77   381.2 2678.05
   387.6 2675.38   393.4 2674.17     401 2674.33     405 2675.25   412.3 2678.31
   416.6  2678.8     447 2678.74   463.5 2677.43   480.3 2680.35   538.3 2679.14
   602.1 2679.69   631.9 2680.85   660.4 2683.39   679.9 2686.28   748.9 2701.73
#Mann= 7 ,-1,0
       0      .1       0     260     .05       0     340      .1       0
   387.6    .045       0     405      .1       0     540     .12       0
     620     .05       0
#XS Ineff= 2 , 0
          372.86 2681.37  442.07         2682.11
Permanent Ineff=
       F       F
Bank Sta=387.6,405
XS Rating Curve= 0 ,0
Exp/Cntr=0.3,0.1

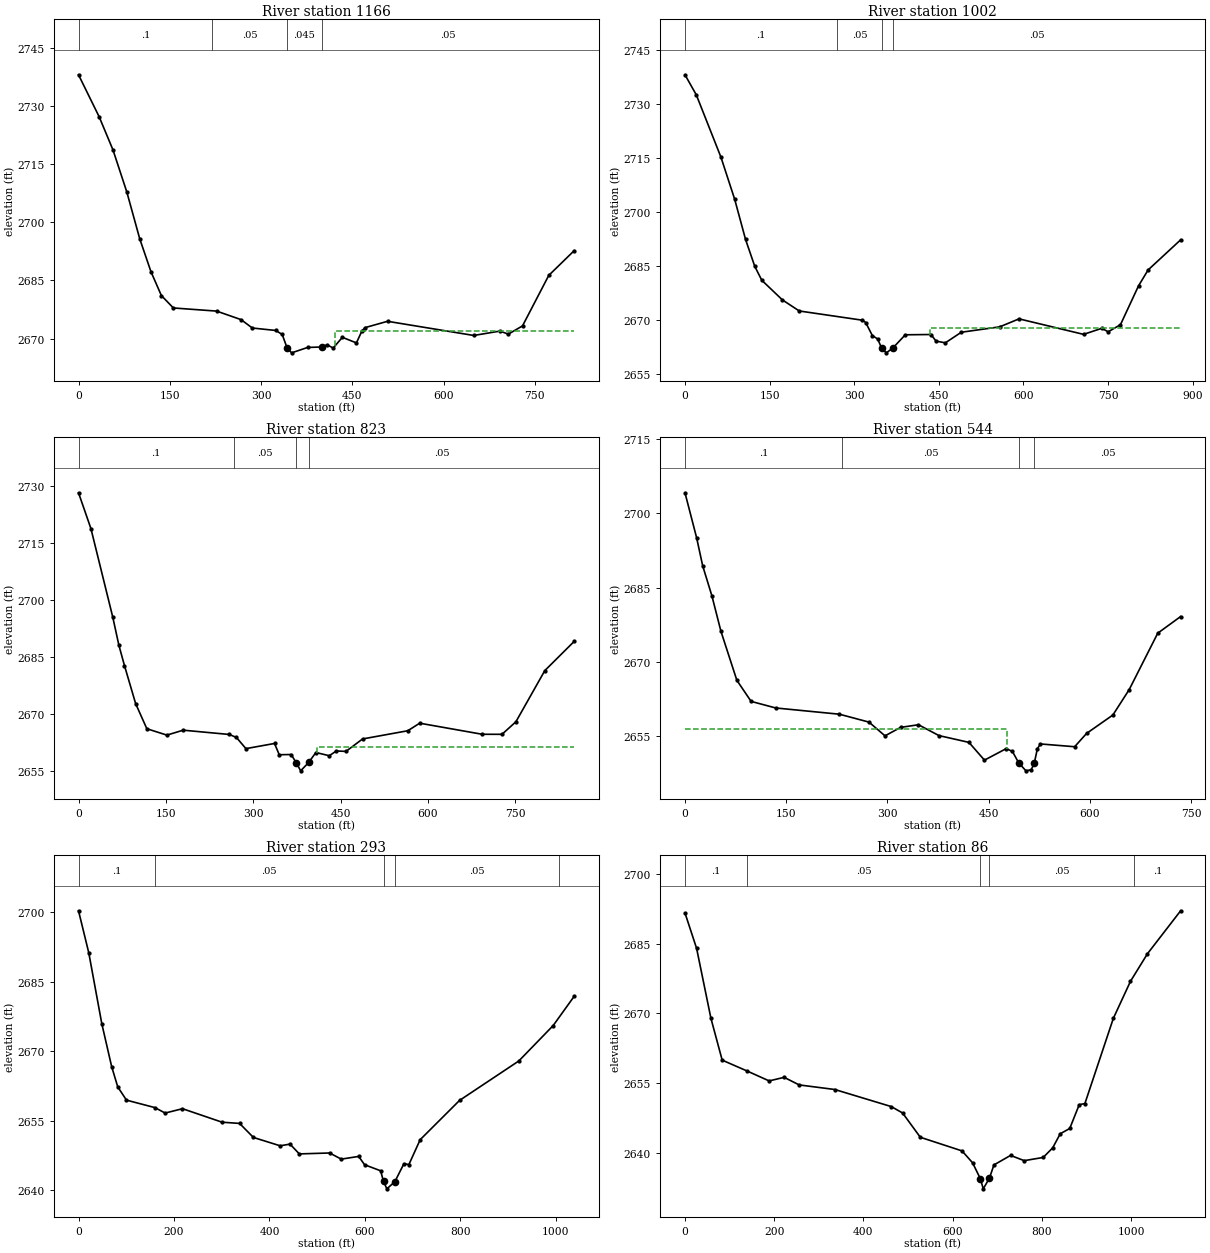
Type RM Length L Ch R = 1 ,1166    ,153.3,164.5,162.7
XS GIS Cut Line= 2
2304434.94557323495322.4703120922304963.23021336495942.698296665
#Sta/Elev= 30
       0 2738.03      34 2727.18    56.7 2718.64    79.4 2707.81   100.6 2695.76
   119.1 2687.25   136.2 2681.11   155.9 2677.91     227  2677.1   267.2  2674.9
   285.7 2672.74   324.1 2672.11   334.8 2671.08  342.692667.671   350.3 2666.34
   376.6 2667.73     400 2667.85   408.6 2668.42   418.6 2667.57   433.7 2670.34
   456.8  2668.9   465.9    2672   471.2 2672.85   507.9 2674.47   649.6 2670.82
   692.8 2671.95   706.5 2671.16   729.8 2673.29     773 2686.32   814.7 2692.68
#Mann= 4 ,-1,0
       0      .1       0     220     .05       0  342.69    .045       0
     400     .05       0
#XS Ineff= 2 , 0
                          422.01         2671.86
Permanent Ineff=
       F       F
Bank Sta=342.69,400
XS Rating Curve= 0 ,0
Exp/Cntr(USF)=0,0
Exp/Cntr=0.3,0.1

Type RM Length L Ch R = 1 ,1002    ,186.8,178.4,170.6
XS GIS Cut Line= 2
2304285.34284328495431.5556360122304930.50461618 496028.40819403
#Sta/Elev= 30
       0 2738.14    20.1 2732.56    63.8 2715.25    88.1 2703.59   107.4 2692.43
   123.7 2684.97   136.2 2681.09   172.8 2675.63   202.7 2672.56   314.6    2670
   320.5 2669.35   332.2 2665.74   341.7 2664.78   348.5 2662.33     357 2660.94
   368.3 2662.24   390.7 2665.95   436.2 2666.03   445.2  2664.2   461.7 2663.72
     490 2666.66   557.9 2668.15   592.4 2670.37   706.8 2666.07   739.1 2667.75
   750.4 2666.78   772.2 2668.75   804.2 2679.53   821.2 2683.95   878.9 2692.31
#Mann= 4 ,-1,0
       0      .1       0     270     .05       0   348.5    .045       0
   368.3     .05       0
#XS Ineff= 2 , 0
                          434.83         2667.79
Permanent Ineff=
       F       F
Bank Sta=348.5,368.3
XS Rating Curve= 0 ,0
Exp/Cntr(USF)=0,0
Exp/Cntr=0.3,0.1

Type RM Length L Ch R = 1 ,823     ,274.6,279.6,285.4
XS GIS Cut Line= 4
2304154.44045458495688.6853281082304335.21041993 495808.67918442
2304707.65888303495886.5972729342304886.87048661496065.808876517
#Sta/Elev= 30
       0 2728.28    21.3 2718.85    58.8 2695.53    69.3 2688.12    78.9 2682.76
    98.1 2672.73   117.3 2666.13   151.7 2664.45   179.7 2665.75   258.9 2664.62
   271.1 2663.83   287.4 2660.89   336.5 2662.25   344.6 2659.28   365.1 2659.34
   373.7 2657.19   381.4 2655.04   395.2 2657.26   407.5 2659.87   430.5 2659.02
   442.7 2660.28   459.1 2660.16   487.7 2663.44   565.3  2665.6   585.7 2667.59
     693 2664.67     727 2664.66   750.9 2667.97   800.5 2681.44   850.9 2689.13
#Mann= 4 ,-1,0
       0      .1       0  266.97     .05       0   373.7    .045       0
   395.2     .05       0
#XS Ineff= 2 , 0
                          408.78         2661.43
Permanent Ineff=
       F       F
Bank Sta=373.7,395.2
XS Rating Curve= 0 ,0
Exp/Cntr(USF)=0,0
Exp/Cntr=0.3,0.1

Type RM Length L Ch R = 1 ,544     ,249.7,250.2,252.9
XS GIS Cut Line= 3
2304160.67390166495777.5119490152304260.40905496495976.982255611
2304704.54215949496230.995224167
#Sta/Elev= 30
       0 2704.18    17.3 2695.07    26.2 2689.45    39.9 2683.36    53.3  2676.2
    76.9  2666.3      98 2662.04   134.5 2660.71   228.9 2659.45   272.8 2657.85
   296.5 2655.08   319.7 2656.79   346.1 2657.32   376.5 2655.13   420.9 2653.76
   443.9 2650.17   476.2  2652.5   485.4 2651.92   494.6 2649.64   505.4 2648.01
   513.2 2648.24   517.7 2649.51   522.3 2652.46   526.9 2653.44   577.6 2652.88
   595.3 2655.57   634.3 2659.29   658.5 2664.43   700.8 2675.82   734.7 2679.18
#Mann= 4 ,-1,0
       0      .1       0  233.01     .05       0   494.6    .045       0
   517.7     .05       0
#XS Ineff= 2 , 0
          476.85 2656.44
Permanent Ineff=
       F       F
Bank Sta=494.6,517.7
XS Rating Curve= 0 ,0
Exp/Cntr(USF)=0,0
Exp/Cntr=0.3,0.1

Type RM Length L Ch R = 1 ,293     ,202.5,207.5,214.4
XS GIS Cut Line= 4
2304087.43089846495833.6129727452304261.96741673496232.553585937
2304500.39676758496399.2982953572304812.06912164496408.648465979
#Sta/Elev= 30
       0 2700.33    21.5 2691.25    48.8 2675.91    69.4 2666.66    82.2 2662.26
   100.5  2659.4     1602657.788   181.5 2656.61   217.8 2657.55   300.8 2654.63
   337.4 2654.37   366.3 2651.34   422.4 2649.53     443  2649.9   462.5 2647.78
     526 2647.98   550.4 2646.65   586.8 2647.24   599.2 2645.44   632.8 2644.13
   638.9 2641.82   645.9 2640.23   662.7 2641.79   681.6 2645.66     692 2645.48
   715.7 2650.86   798.2 2659.35   922.3 2667.87   994.3 2675.53  1038.2 2681.84
#Mann= 5 ,-1,0
       0      .1       0     160     .05       0   638.9    .045       0
   662.7     .05       0  1006.4      .1       0
Bank Sta=638.9,662.7
XS Rating Curve= 0 ,0
Exp/Cntr(USF)=0,0
Exp/Cntr=0.3,0.1

Type RM Length L Ch R = 1 ,86      ,,,
XS GIS Cut Line= 4
 2304064.0554719495853.8716757582304260.40905496496453.840957317
2304307.15990807 496525.52559875 2304678.0500094496659.544710994
#Sta/Elev= 30
       0 2691.57    26.1 2683.94    58.2  2668.9    83.4 2659.92     140 2657.55
   188.7 2655.45   222.3 2656.22     256 2654.59     336  2653.6   462.5 2649.93
   487.9 2648.55   527.6 2643.33   621.1  2640.4   644.8 2637.84   662.4 2634.37
   668.7 2632.24   682.7 2634.57   692.6 2637.38   729.9 2639.43   760.5  2638.3
     803 2638.99   824.3 2641.04   841.3 2644.09   862.6 2645.22   883.8 2650.33
   896.6 2650.59   960.4 2668.92   998.8 2676.88  1036.9 2682.81  1111.2 2692.04
#Mann= 5 ,-1,0
       0      .1       0     140     .05       0   662.4    .045       0
   682.7     .05       0 1006.87      .1       0
Bank Sta=662.4,682.7
XS Rating Curve= 0 ,0
Exp/Cntr(USF)=0,0
Exp/Cntr=0.3,0.1
LCMann Table=0

Chan Stop Cuts=-1
Use User Specified Reach Order=0
Composite Channel Slope=5